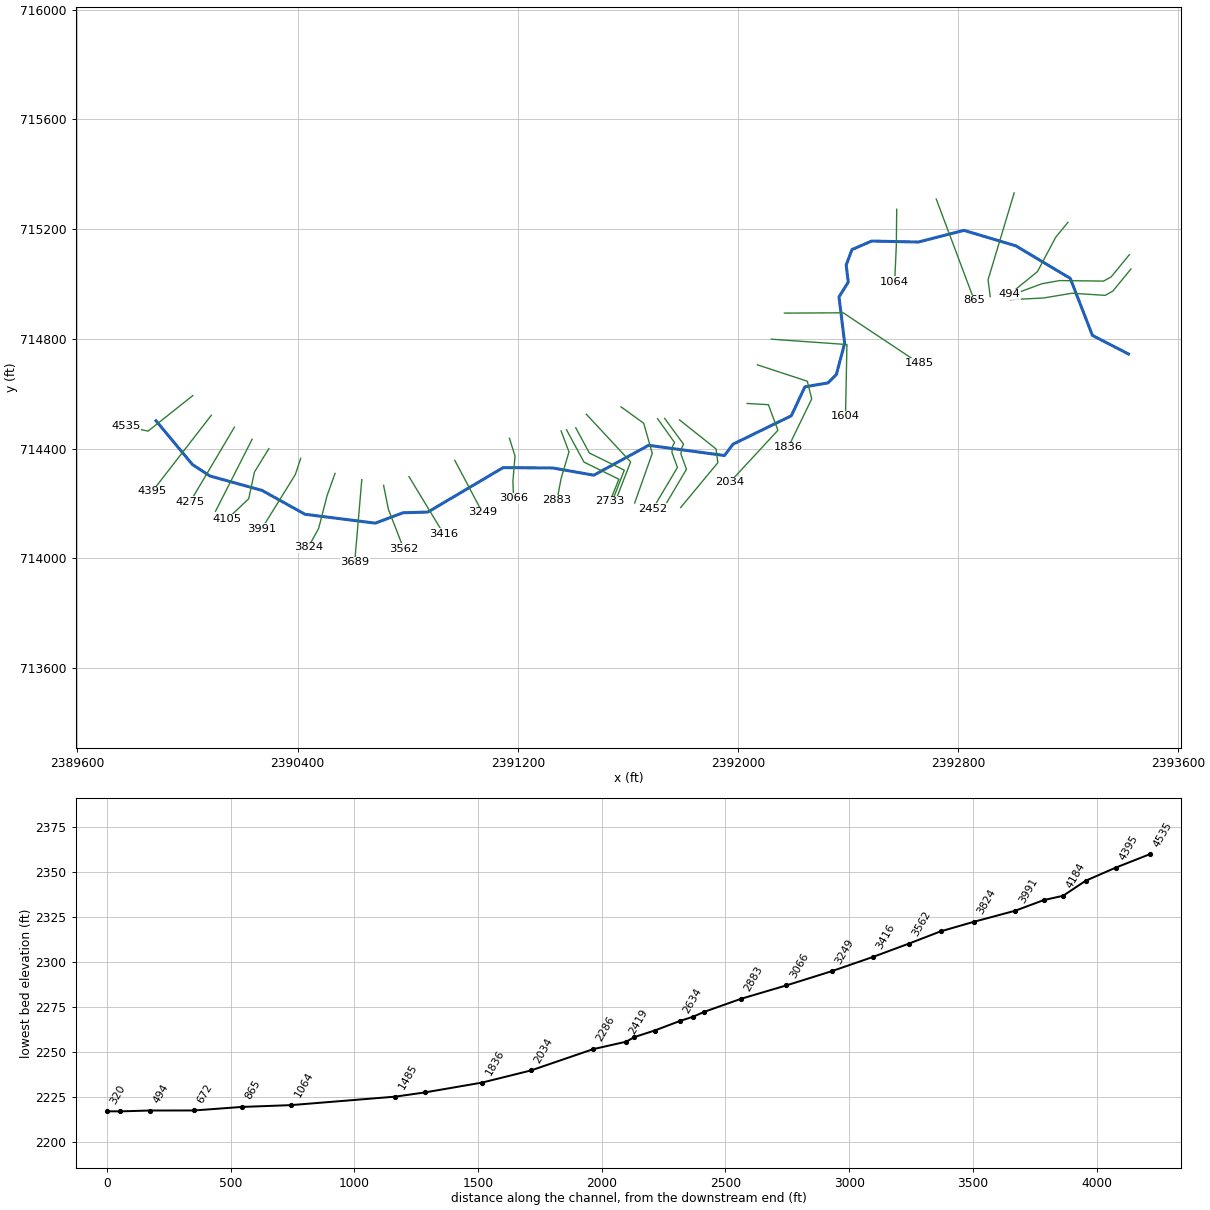
--- DRKFK_2T1.prj (project) ---

Proj Title=DRKFK_2T1
Current Plan=p01
Default Exp/Contr=0,0
English Units
Geom File=g01
Flow File=f01
Plan File=p01
BEGIN DESCRIPTION:
----------MODEL BY WOOD PLC 2022----------
AFH study
Randolph County, WV
HEC-RAS Version: RAS 6.2
Vertical Datum: NAVD88
Projection: NAD 1983 StatePlane West Virginia S FIPS 4702 (US Feet)
Terrain: 1-meter LIDAR (FEMA Region III 3DEP collected 2016-2018)
Land Use: 2019 NLCD
Hydrologic Method:
WV SIR2010-5033 regression equations
Additional Model Notes:
Main stem dominates backwater DS of XS 1604
END DESCRIPTION:
DSS Export Rating Curves= 0
DSS Export Rating Curve Sorted= 0
DSS Export Volume Flow Curves= 0
DXF OffsetX= 0
DXF OffsetY= 0
DXF ScaleX= 0
DXF ScaleY= 0

--- DRKFK_2T1.p01 (plan) ---

Plan Title=Floodplain
Program Version=6.20
Short Identifier=Floodplain
Geom File=g01
Flow File=f01
Subcritical Flow
K Sum by GR= 0
Std Step Tol= 0.01
Critical Tol= 0.01
Num of Std Step Trials= 20
Max Error Tol= 0.3
Flow Tol Ratio= 0.001
Split Flow NTrial= 30
Split Flow Tol= 0.02
Split Flow Ratio= 0.02
Log Output Level= 0
Friction Slope Method= 1
Unsteady Friction Slope Method= 2
Unsteady Bridges Friction Slope Method= 1
Parabolic Critical Depth
Global Vel Dist= 0 , 0 , 0
Global Log Level= 0
CheckData=True
Encroach Param=-1 ,0,0, 0
Mapping Interval=1HOUR
Computation Time Step Use Courant=        0
Computation Time Step Use Time Series=    0
Computation Time Step Count To Double=0
Computation Time Step Max Doubling=0
Computation Time Step Max Halving=0
Computation Time Step Residence Courant=0
Run HTab= 0
Run UNet= 0
Run Sediment= 0
Run PostProcess= 0
Run WQNet= 0
Run RASMapper=-1
UNET Theta= 0
UNET Theta Warmup= 0
UNET ZTol= 0
UNET ZSATol= 0
UNET MxIter= 0
UNET Max Iter WO Improvement= 0
UNET MaxInSteps= 0
UNET DtIC= 0
UNET DtMin= 0
UNET MaxCRTS= 0
UNET WFStab= 0
UNET SFStab= 0
UNET WFX= 1
UNET SFX= 1
UNET Gravity=32.174
UNET 1D Methodology=Finite Difference
UNET DSS MLevel= 1
UNET Pardiso=0
UNET DZMax Abort= 0
UNET Use Existing IB Tables= 0
UNET Froude Reduction=False
UNET Froude Limit= 0
UNET Froude Power= 0
UNET D1 Cores= 0
UNET WindReference=Eulerian
UNET WindDragFormulation=Hsu (1988)
UNET D2 Coriolis=0
UNET D2 Cores= 0
UNET D2 Theta= 1
UNET D2 Theta Warmup= 1
UNET D2 Z Tol= 0.01
UNET D2 Volume Tol= 0.01
UNET D2 Max Iterations= 20
UNET D2 Equation= 0
UNET D2 RampUpFraction=0.1
UNET D2 TimeSlices= 1
UNET D2 Turbulence Formulation=Non-Conservative (original)
UNET D2 Eddy Viscosity=0.3
UNET D2 Transverse Eddy Viscosity=0.1
UNET D2 Smagorinsky Mixing=0
UNET D2 BCVolumeCheck=0
UNET D2 Cores=0
UNET D2 SolverType=PARDISO (Direct)
UNET D2 Minimum Iterations= 2147483647
UNET D2 Maximum Iterations= 2147483647
UNET D2 Restart Number= 10
UNET D2 Relaxation Coeff=1.3
UNET D2 SOR Precondition Iterations= 10
UNET D2 ILUT Maximum Fill= 8
UNET D2 ILUT Tolerance=1E-08
UNET D1D2 MaxIter= 0
UNET D1D2 ZTol=0.01
UNET D1D2 QTol=0.1
UNET D1D2 MinQTol=1
Write IC File= 0
Write IC File at Fixed DateTime=0
Write IC File at Sim End=0
Echo Input=False
Echo Parameters=False
Echo Output=False
Write Detailed= 0
HDF Write Warmup=0
HDF Write Time Slices=0
HDF Flush=0
HDF Compression= 1
HDF Chunk Size= 1
HDF Spatial Parts= 1
HDF Use Max Rows=0
HDF Fixed Rows= 1
Calibration Method= 0
Calibration Iterations= 20
Calibration Max Change=0.05
Calibration Tolerance=0.2
Calibration Maximum=1.5
Calibration Minimum=0.5
Calibration Optimization Method= 1
WQ AD Non Conservative
WQ ULTIMATE=-1
WQ Max Comp Step=1HOUR
WQ Output Interval=15MIN
WQ Output Selected Increments= 0
WQ Output face flow=0
WQ Output face velocity=0
WQ Output face area=0
WQ Output face dispersion=0
WQ Output cell volume=0
WQ Output cell surface area=0
WQ Output cell continuity=0
WQ Output cumulative cell continuity=0
WQ Output face conc=0
WQ Output face dconc_dx=0
WQ Output face courant=0
WQ Output face peclet=0
WQ Output face adv mass=0
WQ Output face disp mass=0
WQ Output cell mass=0
WQ Output cell source sink temp=0
WQ Output nsm pathways=0
WQ Output nsm derived pathways=0
WQ Create Restart=0
WQ Fixed Restart=0
WQ System Summary=0
WQ Write To DSS=0
Sorting and Armoring Iterations= 10
XS Update Threshold= 0.02
Bed Roughness Predictor= 0
Hydraulics Update Threshold= 0.02
Energy Slope Method= 1
Volume Change Method= 1
Sediment Retention Method= 0
Sediment TS Multiplier= 1
Warm Up Method= 0
XS Weighting Method= 0
Number of US Weighted Cross Sections= 1
Number of DS Weighted Cross Sections= 1
Upstream XS Weight=0
Main XS Weight=1
Downstream XS Weight=0
Number of DS XS's Weighted with US Boundary= 1
Upstream Boundary Weight= 1
Weight of XSs Associated with US Boundary= 0
Number of US XS's Weighted with DS Boundary= 1
Downstream Boundary Weight= 0.5
Weight of XSs Associated with DS Boundary= 0.5
Percentile Method= 0
Sediment Output Level= 3
Mass or Volume Output= 0
Output Increment Type= 1
Profile and TS Output Increment= 1
Transport Output Increment 1
XS Output Flag= 0
XS Output Increment= 10
Read HDF5 Sediment Hotstart= 0
Sediment Hotstart Type= 0
Write Gradation File= 0
Read Gradation Hotstart= 0
Write HDF5 File= 1
Write Binary Output= 1
Write DSS Sediment File= 0
DSS Sediment Output Type= 1
SV Curve= 0
Specific Gage Flag= 0
Subcell Erosion Methods= 0
Subcell Deposition Methods= 0
Advection Scheme= 1
Matrix Solver= 0
Implicit Weighting Factor= 1
Maximum Outer Loop Convergence Iterations= 5
Convergence Maximum Absolute= 0.001
Convergence RMSE= 0.0001
Grain Fractions Max Abs Error= 0.001
Max Subgrid Regions= 1
Max Subgrid Length Scale= 3.402823E+38
Initial Layer Thickness= 3.402823E+38
Min Layer Thickness= 3.402823E+38
Max Layer Thickness= 3.402823E+38
Number of Layers= 5

--- DRKFK_2T1.f01 (steady flow) ---

Flow Title=Flow
Program Version=6.20
Number of Profiles= 1
Profile Names=P100yr
River Rch & RM=DRKFK_2T1,Main,4535
     361
Boundary for River Rch & Prof#=DRKFK_2T1,Main            , 1
Up Type= 0
Dn Type= 3
Dn Slope=0.00863
DSS Import GetInterval= 0
DSS Import GetPeak= 0
DSS Import FillOption= 0

--- DRKFK_2T1.g01 (geometry) ---

Geom Title=Geometry
Program Version=6.20

River Reach=DRKFK_2T1       ,Main
Reach XY= 30
 2389885.5137082714501.692063451     2390017.743      714342.351
     2390081.399      714300.431      2390270.63      714247.934
      2390426.88      714160.955     2390682.404      714128.674
2390783.01367147714166.456053866 2390873.4806176714169.098201068
     2391146.655      714330.994     2391327.525      714329.706
     2391476.359      714303.403     2391675.318      714412.257
 2391951.0310736714375.068402135     2391981.977      714416.373
     2392194.068       714520.07     2392243.104      714625.269
2392327.19086123 714639.744564612392357.43810142714670.101141353
     2392387.817      714784.1322392367.18120139714953.023935506
     2392400.838      715007.0492392393.28714954715069.116295856
  2392414.251017715125.4814111882392485.64682975715156.531667705
2392655.39944975715153.008550253     2392821.255715195.456675162
     2393009.731      715139.0682393207.46607672715020.656768661
     2393287.922      714812.848     2393418.842      714745.049

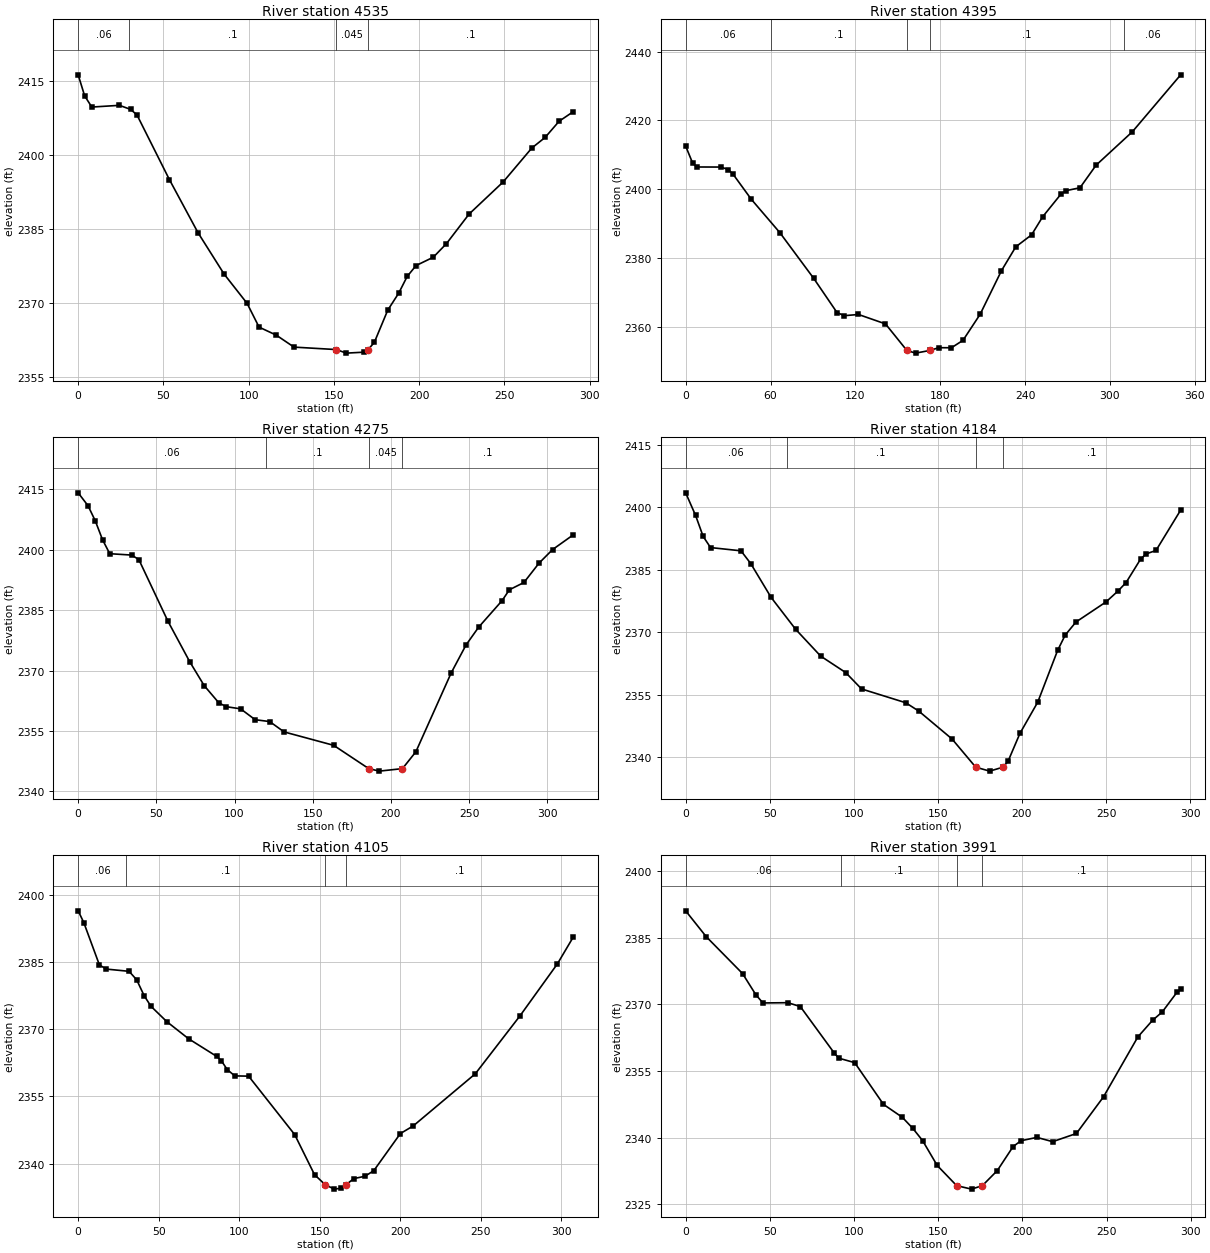
Type RM Length L Ch R = 1 ,4535    ,135.7,137.8,139.7
XS GIS Cut Line= 3
2390019.13391273714593.4476849592389856.67504891714463.900746143
2389776.14587073 714482.10734295
#Sta/Elev= 30
       0 2416.29     3.8 2412.02       8 2409.75    24.2  2410.1    30.8 2409.27
    34.5 2408.15    53.5 2395.04    70.3 2384.25    85.6 2375.86    99.1 2369.91
   106.1  2365.1   116.2 2363.47   126.6 2361.04  151.412360.542   157.3 2359.82
   167.4 2360.01  170.062360.542   173.7 2361.99   181.6 2368.55     188 2371.98
     193 2375.39   198.2 2377.59   208.3 2379.28     216 2382.03   229.3 2388.04
   249.3 2394.56   266.1 2401.44   273.9 2403.59   282.1 2406.87290.3483  2408.8
#Mann= 4, -1 ,  0
       0    0.06       0      30     0.1       0  151.41   0.045       0
  170.06     0.1       0
Bank Sta=151.41,170.06
XS Rating Curve= 0 ,0
Exp/Cntr(USF)=0,0
Exp/Cntr=0.3,0.1

Type RM Length L Ch R = 1 ,4395    ,119.7,122.3,123
XS GIS Cut Line= 2
2390086.57587448714521.8516682012389872.48750574714244.965102311
#Sta/Elev= 30
       0 2412.53       5 2407.53     7.9 2406.46      25 2406.44    30.1 2405.71
    33.6 2404.32    46.4 2397.08    66.6 2387.38    90.6 2374.06     107 2364.17
   112.1 2363.25   122.2  2363.6   141.3 2360.86  156.412353.146   162.6 2352.37
  172.632353.145     179 2353.95   187.9 2353.93   196.1 2356.09   208.2 2363.65
   223.3 2376.33   233.4 2383.25   244.6 2386.75   252.4 2391.98   265.5 2398.65
   268.8 2399.57   278.8 2400.42   290.2 2406.98   315.9 2416.72     350 2433.24
#Mann= 5, -1 ,  0
       0    0.06       0      60     0.1       0  156.41   0.045       0
  172.63     0.1       0     310    0.06       0
Bank Sta=156.41,172.63
XS Rating Curve= 0 ,0
Exp/Cntr(USF)=0,0
Exp/Cntr=0.3,0.1

Type RM Length L Ch R = 1 ,4275    ,89.7,90.9,91.4
XS GIS Cut Line= 2
2390170.57863321714478.5874576282390009.46157318714206.045949651
#Sta/Elev= 30
       0 2414.15     6.3 2410.95    10.9 2407.23    15.6 2402.49    20.2 2399.03
    34.2 2398.69    38.8 2397.58    57.4 2382.27    71.3 2372.24    80.6 2366.27
    89.9 2362.02    94.6 2361.04   103.9  2360.5   113.2  2357.8   122.5 2357.34
   131.7 2354.77   163.4 2351.44  185.852345.653   192.6 2345.03  207.412345.652
     216 2349.84   238.6 2369.44   248.1 2376.38   256.2 2380.81   271.1 2387.36
   275.8 2390.07   285.1 2391.88   294.8  2396.7   303.4 2400.05316.6032  2403.7
#Mann= 4, -1 ,  0
       0    0.06       0     120     0.1       0  185.85   0.045       0
  207.41     0.1       0
Bank Sta=185.85,207.41
XS Rating Curve= 0 ,0
Exp/Cntr(USF)=0,0
Exp/Cntr=0.3,0.1

Type RM Length L Ch R = 1 ,4184    ,77.3,79.1,81.4
XS GIS Cut Line= 2
2390234.81205951714434.4900897632390101.76385208714171.894943513
#Sta/Elev= 30
       0 2403.43     5.9 2398.02    10.4 2392.98    14.8 2390.31    32.9 2389.53
    38.7 2386.48    50.8 2378.37    65.4 2370.72    80.3 2364.29    95.2 2360.34
   104.6 2356.42   130.9 2353.11   138.6 2351.12   158.4 2344.43   172.52337.666
   180.8 2336.72  188.692337.666   191.7 2339.06   198.8 2345.77   209.4 2353.27
   221.2 2365.66   225.7 2369.32   232.1 2372.46     250 2377.28   257.1 2379.89
   261.9 2381.91   270.5 2387.51   273.8 2388.79   279.7 2389.61294.3774 2399.29
#Mann= 4, -1 ,  0
       0    0.06       0      60     0.1       0   172.5   0.045       0
  188.69     0.1       0
Bank Sta=172.5,188.69
XS Rating Curve= 0 ,0
Exp/Cntr(USF)=0,0
Exp/Cntr=0.3,0.1

Type RM Length L Ch R = 1 ,4105    ,115.9,114.1,111
XS GIS Cut Line= 4
2390295.41321187714400.1283290342390243.21510419714314.746703073
2390222.20749249 714217.411435532390144.17344252714143.298692589
#Sta/Elev= 30
       0 2396.44     3.5 2393.81    13.2 2384.34    17.5 2383.43    31.6 2382.93
    36.3 2381.05      41 2377.46    45.2 2375.12      55  2371.7    68.5 2367.88
      86 2363.93    88.9 2362.96    92.5    2361    97.2 2359.58   105.8 2359.52
   134.4 2346.47   146.7 2337.53  153.362335.265     159 2334.29   163.1 2334.49
  166.192335.265   171.2 2336.65     178 2337.16   183.5 2338.41     200  2346.7
     208 2348.41   246.5 2360.04   274.2 2372.96   297.5 2384.61307.2695 2390.55
#Mann= 4, -1 ,  0
       0    0.06       0      30     0.1       0  153.36   0.045       0
  166.19     0.1       0
Bank Sta=153.36,166.19
XS Rating Curve= 0 ,0
Exp/Cntr(USF)=0,0
Exp/Cntr=0.3,0.1

Type RM Length L Ch R = 1 ,3991    ,165.2,167.7,169.8
XS GIS Cut Line= 3
2390411.29094462714364.7489754652390391.66889354 714305.64340467
2390269.83857801714108.508444075
#Sta/Elev= 30
       0 2391.06    12.2 2385.25    33.8 2376.94    41.7 2372.17    45.9 2370.33
    60.7 2370.39    68.1 2369.52    88.4 2358.99      91  2357.9   100.4  2356.9
   117.5 2347.51   128.7  2344.6   134.9 2342.12   140.7 2339.38   149.4 2333.77
  160.962329.221   169.8 2328.44  176.242329.224   185.1 2332.61   194.5 2338.02
   199.2 2339.33   208.6 2340.08     218 2339.12   232.1 2340.96   248.2 2349.21
   268.6 2362.69   277.3 2366.42   283.1 2368.31   291.8 2372.72294.0205 2373.37
#Mann= 4, -1 ,  0
       0    0.06       0   92.28     0.1       0  160.96   0.045       0
  176.24     0.1       0
Bank Sta=160.96,176.24
XS Rating Curve= 0 ,0
Exp/Cntr(USF)=0,0
Exp/Cntr=0.3,0.1

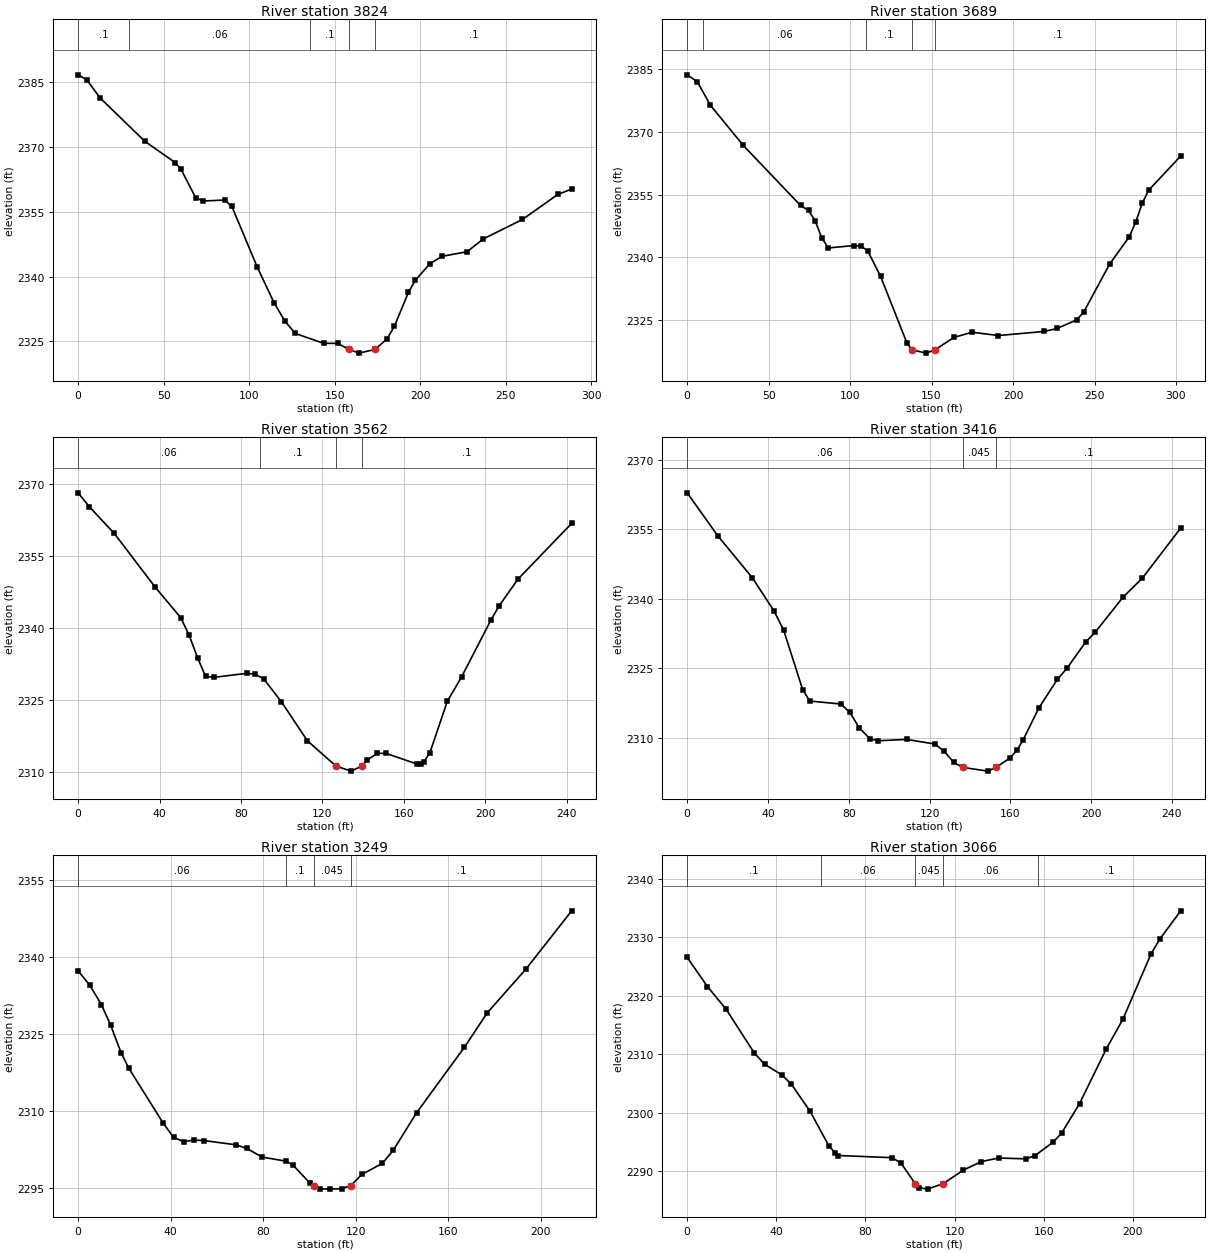
Type RM Length L Ch R = 1 ,3824    ,133,134.5,135.7
XS GIS Cut Line= 4
2390535.96672945 714309.925207452390507.21075789714229.315748827
2390476.39959406714109.5723621372390438.38636813714039.939098383
#Sta/Elev= 30
       0 2386.71       5  2385.6    12.9 2381.34      39 2371.32    56.8 2366.38
    60.2  2364.8    68.7 2358.29      73 2357.49    85.7 2357.72    89.9 2356.24
   104.6 2342.31   114.6 2333.91     121 2329.63     127 2326.82   143.6 2324.54
   151.8 2324.52  158.332323.132   164.2 2322.27  173.652323.132   180.7 2325.61
   184.9 2328.47   193.1 2336.33   197.2 2339.16   205.5  2342.9   212.6 2344.67
   227.4 2345.75     237 2348.74   259.8 2353.22   280.4    2359288.5623 2360.27
#Mann= 5, -1 ,  0
       0     0.1       0      30    0.06       0  135.58     0.1       0
  158.33   0.045       0  173.65     0.1       0
Bank Sta=158.33,173.65
XS Rating Curve= 0 ,0
Exp/Cntr(USF)=0,0
Exp/Cntr=0.3,0.1

Type RM Length L Ch R = 1 ,3689    ,125.2,127.2,131
XS GIS Cut Line= 2
2390633.25642809714287.4368078632390607.34704033713985.627453107
#Sta/Elev= 30
       0 2383.72     6.3 2382.03    14.3  2376.4    34.4  2366.8    69.6 2352.37
    74.5 2351.18    78.5 2348.75    82.6 2344.64    86.6 2342.18   102.6 2342.77
   106.6  2342.6   110.7 2341.56   118.7 2335.37   134.8 2319.45  137.94 2317.74
   146.8 2316.95  152.05 2317.74   163.8 2320.74   174.9 2321.96     191 2321.17
   219.1 2322.15   227.1 2322.87   239.1 2324.93   243.4 2326.82   259.2 2338.26
   271.3 2344.85   275.3 2348.39   279.3 2352.94   283.3 2356.07302.9194 2364.24
#Mann= 5, -1 ,  0
       0     0.1       0      10    0.06       0     110     0.1       0
  137.94   0.045       0  152.05     0.1       0
Bank Sta=137.94,152.05
XS Rating Curve= 0 ,0
Exp/Cntr(USF)=0,0
Exp/Cntr=0.3,0.1

Type RM Length L Ch R = 1 ,3562    ,142.3,145.9,145.8
XS GIS Cut Line= 3
  2390712.356561714266.6037617872390729.89144191714178.897480747
2390785.15318445714036.142601011
#Sta/Elev= 30
       0 2368.26     5.5 2365.37    17.8 2359.78    37.7 2348.68    50.4 2342.23
    54.5 2338.62    58.8 2333.75    62.6 2329.98    66.7 2329.76      83 2330.61
    87.1  2330.4    91.3  2329.4    99.9 2324.66   112.7 2316.51  126.722311.246
   134.2  2310.2  139.352311.249     142 2312.48     147 2313.93   151.4 2313.89
   166.7 2311.65   168.5  2311.6   169.8  2312.1   172.8    2314   181.4 2324.77
   188.4 2329.85   202.8 2341.69   206.9 2344.71   216.2 2350.29   242.5 2361.89
#Mann= 4, -1 ,  0
       0    0.06       0   89.44     0.1       0  126.72   0.045       0
  139.35     0.1       0
Bank Sta=126.72,139.35
XS Rating Curve= 0 ,0
Exp/Cntr(USF)=0,0
Exp/Cntr=0.3,0.1

Type RM Length L Ch R = 1 ,3416    ,167.4,167,166.5
XS GIS Cut Line= 2
2390804.79230471714298.1131011092390931.08064129714088.940288084
#Sta/Elev= 30
       0 2362.89    15.1 2353.64    32.3 2344.52    43.1  2337.3    47.8 2333.18
    57.2 2320.35    60.7 2317.91      76 2317.27    80.5  2315.5    85.2 2312.09
    90.5 2309.77    94.5 2309.33   108.6 2309.62   122.6 2308.63   127.2 2307.08
   131.9 2304.69  136.322303.583   148.8 2302.77  152.982303.582     160 2305.66
   163.4 2307.37   166.3  2309.5     174 2316.34   183.3 2322.62     188 2324.97
   197.3 2330.68     202 2332.77   215.8 2340.36   225.4 2344.49  244.34 2355.29
#Mann= 3, -1 ,  0
       0    0.06       0  136.32   0.045       0  152.98     0.1       0
Bank Sta=136.32,152.98
XS Rating Curve= 0 ,0
Exp/Cntr(USF)=0,0
Exp/Cntr=0.3,0.1

Type RM Length L Ch R = 1 ,3249    ,187.7,183.5,180.5
XS GIS Cut Line= 2
2390971.04683992714357.670910212 2391070.6051709714168.975654422
#Sta/Elev= 30
       0 2337.35     5.1  2334.5    10.1 2330.75    14.1 2326.72    18.6 2321.37
    21.9 2318.39    36.7 2307.74    41.3 2304.91    45.6 2304.09    50.3 2304.39
    54.5 2304.29    68.4 2303.46    72.9 2302.75    79.6 2301.08      90 2300.27
      93 2299.48   100.1 2296.06  101.792295.544   104.6 2294.89   109.1 2294.84
   113.9 2294.93  117.942295.546   122.6 2297.69   131.5 2299.85   136.2 2302.38
   146.3  2309.7     167 2322.47   176.9 2329.19   193.6 2337.69213.3489 2349.02
#Mann= 4, -1 ,  0
       0    0.06       0      90     0.1       0  101.79   0.045       0
  117.94     0.1       0
Bank Sta=101.79,117.94
XS Rating Curve= 0 ,0
Exp/Cntr(USF)=0,0
Exp/Cntr=0.3,0.1

Type RM Length L Ch R = 1 ,3066    ,184.3,182.5,180.9
XS GIS Cut Line= 4
2391169.72291128714437.8553392952391189.95813814714373.568015833
2391182.25534718 714280.434270632391184.61858923714219.834977862
#Sta/Elev= 30
       0 2326.59     9.1  2321.6    17.5 2317.71    30.1 2310.25    34.8  2308.3
    42.6 2306.46    46.8 2304.88    55.2 2300.24    63.6 2294.34    66.3 2293.21
    67.8  2292.7    91.9 2292.33    95.9 2291.43  102.312287.912   103.9 2287.22
   107.9 2286.95  114.962287.912     124 2290.21     132 2291.66   139.8 2292.27
   152.1 2292.13   156.1 2292.69   164.1 2294.94   168.1 2296.56   176.1 2301.59
   188.1 2310.94   195.6 2316.05   208.1 2327.13   212.1 2329.71   221.5 2334.55
#Mann= 5, -1 ,  0
       0     0.1       0      60    0.06       0  102.31   0.045       0
  114.96    0.06       0   157.4     0.1       0
Bank Sta=102.31,114.96
XS Rating Curve= 0 ,0
Exp/Cntr(USF)=0,0
Exp/Cntr=0.3,0.1

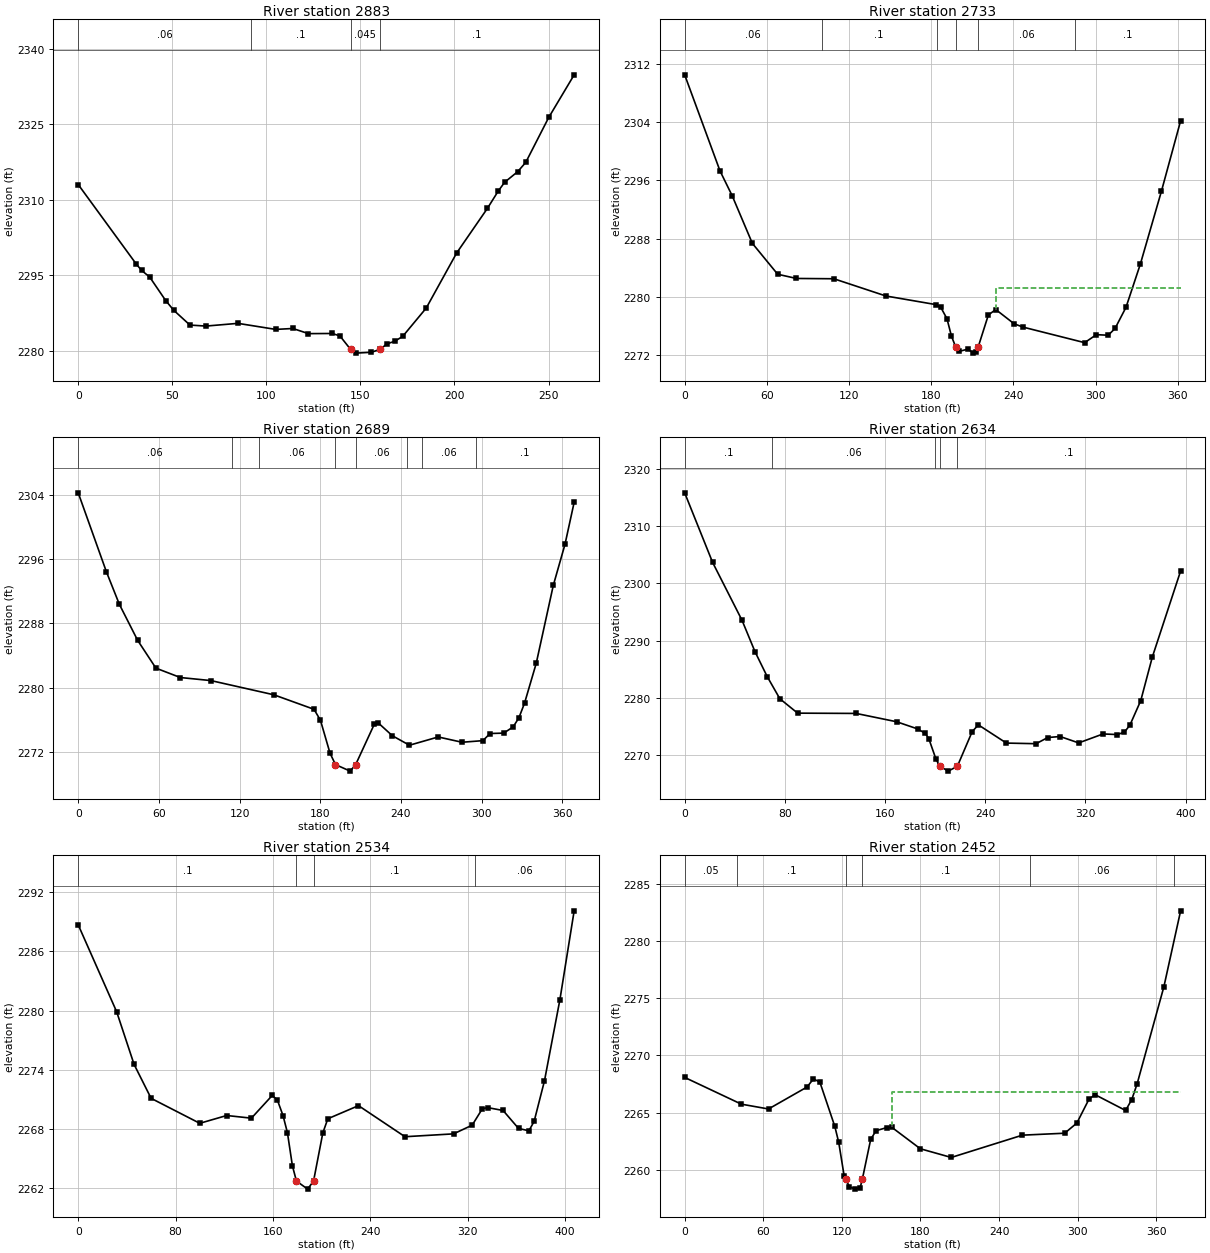
Type RM Length L Ch R = 1 ,2883    ,134.2,149.9,154.6
XS GIS Cut Line= 4
2391357.34109117714464.7545977112391386.02918067714388.273344023
2391357.31877801 714290.938076482391342.32472989714211.886521341
#Sta/Elev= 30
       0 2313.01    30.8 2297.25    33.7 2295.96      38 2294.64    46.5 2289.98
    50.8 2288.04    59.4 2285.11    67.9 2284.91    84.9 2285.45     105 2284.25
   114.1 2284.43   122.4 2283.41     135 2283.44   139.1 2282.96  144.772280.292
   147.5 2279.54   155.8 2279.71  160.53 2280.29   164.1 2281.38   168.3  2281.9
   172.5 2282.87     185 2288.49   201.2 2299.44   217.5 2308.27   223.3 2311.73
   226.7 2313.47   233.6 2315.56   237.9 2317.41   250.1 2326.32263.6269 2334.79
#Mann= 4, -1 ,  0
       0    0.06       0   91.68     0.1       0  144.77   0.045       0
  160.53     0.1       0
Bank Sta=144.77,160.53
XS Rating Curve= 0 ,0
Exp/Cntr(USF)=0,0
Exp/Cntr=0.3,0.1

Type RM Length L Ch R = 1 ,2733    ,46.9,44.1,45.9
XS GIS Cut Line= 4
2391376.96640348714468.9679355422391440.60844988714351.056774123
 2391567.3543738714288.7341927472391534.98699765714208.142723791
#Sta/Elev= 30
       0 2310.53    25.8 2297.31    34.7 2293.89    49.4 2287.35    67.9  2283.1
    81.6 2282.52   108.9 2282.48   146.9 2280.11   183.6 2278.92     187 2278.54
   191.5 2276.98   194.8 2274.57  197.772273.142   200.4 2272.49   206.8  2272.8
   210.8 2272.25   212.8 2272.42  214.372273.146   221.7 2277.49   227.1 2278.25
   240.5 2276.29     247 2275.83     292 2273.69   300.6 2274.79   309.2 2274.71
   314.2 2275.64   322.2 2278.55   332.7 2284.51   348.1 2294.54362.0781 2304.21
#Mann= 6, -1 ,  0
       0    0.06       0     100     0.1       0  183.99    0.06       0
  197.77   0.045       0  214.37    0.06       0  285.23     0.1       0
#XS Ineff= 2 , 0
                          227.25         2281.24
Permanent Ineff=
       F       F
Bank Sta=197.77,214.37
XS Rating Curve= 0 ,0
Exp/Cntr(USF)=0,0
Exp/Cntr=0.3,0.1

Type RM Length L Ch R = 1 ,2689    ,58.1,54.9,52.8
XS GIS Cut Line= 4
2391410.61910341714476.0735953392391460.25607534714384.071821683
2391587.00199927714321.7492403062391542.73030982714206.845338907
#Sta/Elev= 30
       0 2304.29      21 2294.43    30.6 2290.39    44.2  2285.9    57.8 2282.43
      76 2281.26    98.7 2280.88   145.5 2279.11   175.4  2277.3   180.2 2275.93
   187.3 2271.83  191.372270.406   202.3 2269.59   206.42270.406   220.2 2275.42
   223.2  2275.6   233.7    2274   246.4 2272.82   267.8 2273.85   285.5 2273.19
     301 2273.39   306.4 2274.28   316.5 2274.33   323.5  2275.1   327.8 2276.23
     332 2278.06   340.7 2283.03   353.4 2292.75   362.1 2297.87368.9151 2303.11
#Mann= 8, -1 ,  0
       0    0.06       0  114.54     0.1       0  134.54    0.06       0
  191.37   0.045       0   206.4    0.06       0  244.54     0.1       0
  255.78    0.06       0  295.78     0.1       0
Bank Sta=191.37,206.4
XS Rating Curve= 0 ,0
Exp/Cntr(USF)=0,0
Exp/Cntr=0.3,0.1

Type RM Length L Ch R = 1 ,2634    ,102.8,100.7,96.3
XS GIS Cut Line= 3
2391449.05201577714525.5230737962391610.11037214 714351.86015041
2391552.68956682714203.406361063
#Sta/Elev= 30
       0 2315.86    22.3 2303.68    45.8 2293.54    56.2 2288.03    65.9 2283.69
      76 2279.81    90.2 2277.29   136.9 2277.24   169.3 2275.78     186 2274.53
   192.1 2273.75   194.9 2272.85   200.6 2269.28  203.652267.992   210.5 2267.14
  217.752267.993   229.6 2274.06   234.5 2275.24   256.9 2272.05   280.6 2271.94
   289.9 2273.02   299.8  2273.2   314.6 2272.08   334.1 2273.65   345.6 2273.54
   351.2 2273.98   355.5 2275.18   364.2 2279.49   373.4 2287.09396.0233 2302.18
#Mann= 5, -1 ,  0
       0     0.1       0      70    0.06       0     200     0.1       0
  203.65   0.045       0  217.75     0.1       0
Bank Sta=203.65,217.75
XS Rating Curve= 0 ,0
Exp/Cntr(USF)=0,0
Exp/Cntr=0.3,0.1

Type RM Length L Ch R = 1 ,2534    ,84.5,81.3,78.1
XS GIS Cut Line= 4
2391575.21555777  714552.31418112391657.72762532  714492.6111488
2391688.53878915714382.6713142362391624.74776607714202.088819851
#Sta/Elev= 30
       0 2288.69    31.6 2279.88    45.9 2274.55    59.9 2271.11    99.9 2268.58
     122 2269.37   142.3  2269.1   159.4  2271.4   163.6 2270.95   168.3 2269.36
   171.9 2267.63     176 2264.27   179.32262.732   188.5 2261.91  193.382262.735
     201 2267.61   205.1 2269.04   230.3 2270.37   268.5 2267.22   308.4 2267.51
   323.7 2268.39   332.1 2270.06   336.4 2270.17   349.1 2269.88   361.8 2268.06
   370.3 2267.82   374.6 2268.77   383.1 2272.88   395.8 2281.11   407.5 2290.11
#Mann= 4, -1 ,  0
       0     0.1       0   179.3   0.045       0  193.38     0.1       0
  326.02    0.06       0
Bank Sta=179.3,193.38
XS Rating Curve= 0 ,0
Exp/Cntr(USF)=0,0
Exp/Cntr=0.3,0.1

Type RM Length L Ch R = 1 ,2452    ,33.8,33.6,35
XS GIS Cut Line= 6
2391707.94702161 714509.314780832391769.75114108 714422.42020723
2391762.38269901714408.6881106412391759.99397468714387.151086995
2391780.13394582714331.6543980722391690.77763141714181.100699246
#Sta/Elev= 30
       0 2268.08    43.3 2265.74      64 2265.32    93.4 2267.24    98.3 2267.95
   103.2 2267.67   114.6  2263.8   117.6  2262.4   121.7  2259.5  122.832259.179
   125.8 2258.52   129.9 2258.31     134 2258.45  135.622259.179     142 2262.66
   146.1 2263.42   154.2 2263.69   158.2 2263.71   179.9 2261.84   203.5 2261.08
   257.8 2263.03   290.1  2263.2   299.4 2264.09   308.7 2266.19   313.3 2266.57
   336.6 2265.19   341.3 2266.14   345.4 2267.52   365.8    2276   378.6 2282.65
#Mann= 6, -1 ,  0
       0    0.05       0      40     0.1       0  122.83   0.045       0
  135.62     0.1       0  263.49    0.06       0  373.49     0.1       0
#XS Ineff= 2 , 0
                          158.06          2266.8
Permanent Ineff=
       F       F
Bank Sta=122.83,135.62
XS Rating Curve= 0 ,0
Exp/Cntr(USF)=0,0
Exp/Cntr=0.3,0.1

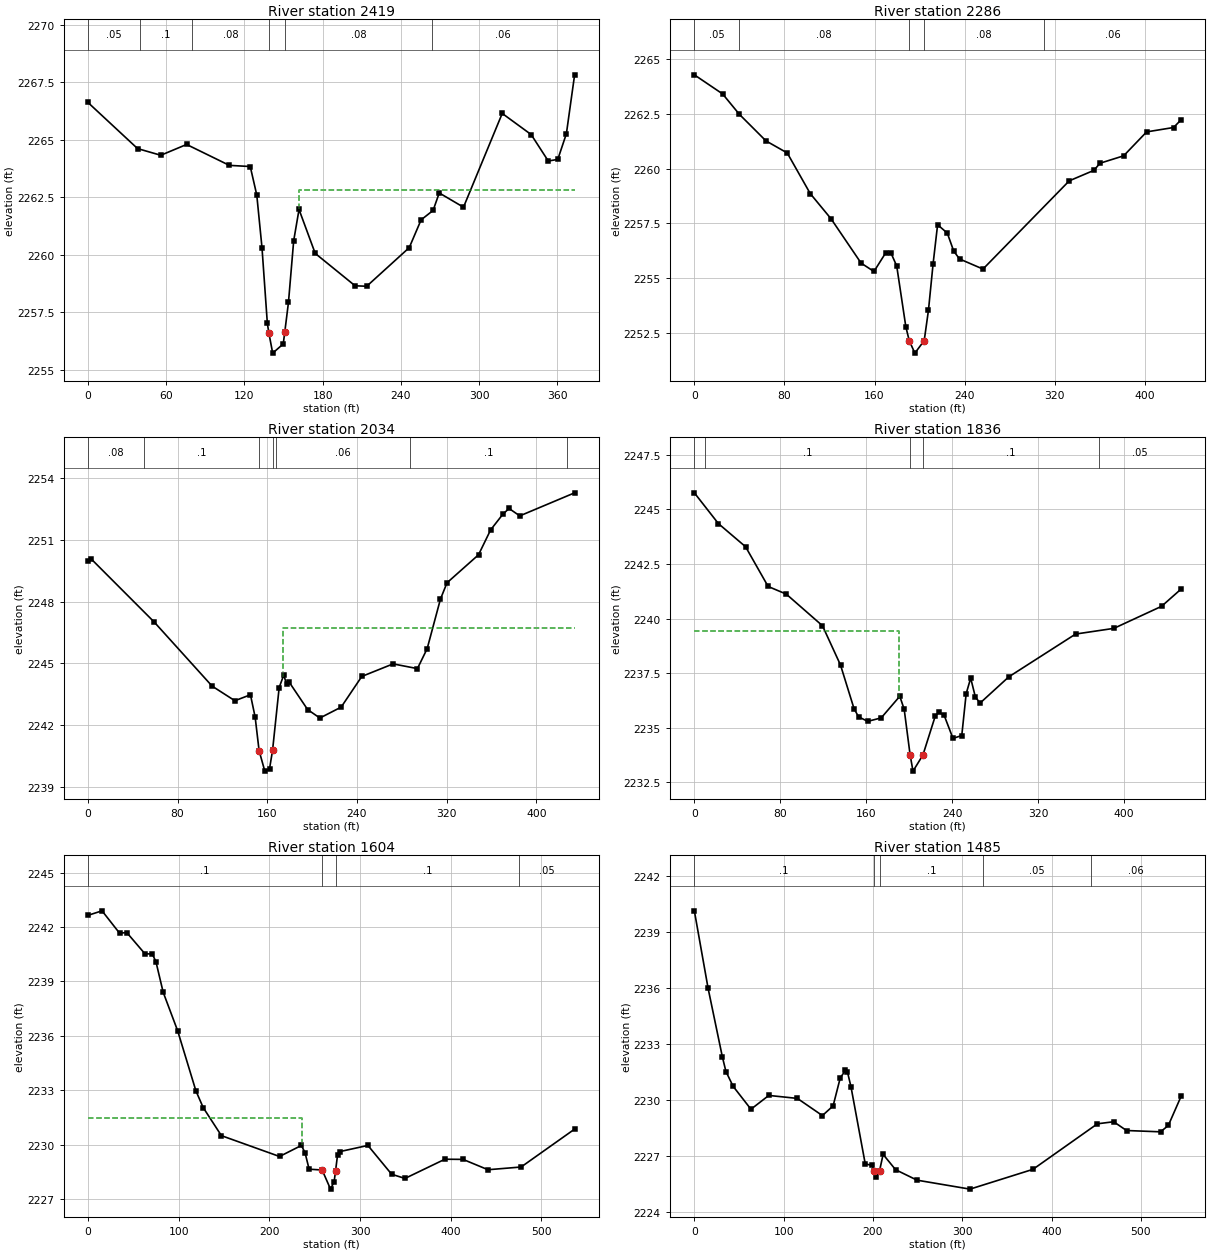
Type RM Length L Ch R = 1 ,2419    ,131.1,133.3,134.1
XS GIS Cut Line= 6
2391733.75887154714510.3939515622391802.56552824714415.796587005
2391795.19708617714402.0644904172391792.80836184 714380.52746677
2391812.94833298714325.0307778482391731.99506326714187.781899764
#Sta/Elev= 30
       0 2266.63    38.1 2264.62    55.9 2264.33    75.7  2264.8   108.5 2263.89
   124.5 2263.84   129.5  2262.6   133.5 2260.31   137.6 2257.02   138.72256.617
   141.7 2255.72   149.8 2256.12  150.93 2256.62   153.8 2257.93   157.8 2260.61
   161.9 2261.97   174.3 2260.06   204.9 2258.65   213.8 2258.63   246.4 2260.31
   255.5 2261.52   264.7 2261.93   269.4 2262.69     288 2262.07   317.7 2266.15
   339.9 2265.23     353 2264.08   360.3 2264.15   366.9 2265.27   373.2 2267.83
#Mann= 6, -1 ,  0
       0    0.05       0      40     0.1       0      80    0.08       0
   138.7   0.045       0  150.93    0.08       0  263.83    0.06       0
#XS Ineff= 2 , 0
                           161.9         2262.83
Permanent Ineff=
       F       F
Bank Sta=138.7,150.93
XS Rating Curve= 0 ,0
Exp/Cntr(USF)=0,0
Exp/Cntr=0.3,0.1

Type RM Length L Ch R = 1 ,2286    ,249.4,251.5,252.6
XS GIS Cut Line= 4
 2391787.6964844714504.8491759072391920.45870258714398.970464321
2391926.97276656 714348.972968242391791.86865275714185.610784439
#Sta/Elev= 30
       0 2264.27    25.1  2263.4      40 2262.47    63.6 2261.26    82.5 2260.71
   102.9 2258.86   121.4 2257.71   148.1 2255.69   159.5 2255.31   169.8 2256.15
   174.7 2256.14   179.7 2255.56   187.8 2252.79   190.8 2252.16   195.8 2251.59
  204.11 2252.16   207.9 2253.55     212 2255.66     216 2257.44   224.6 2257.06
   230.3 2256.24   235.5 2255.88   256.3 2255.42   332.9 2259.44   354.9 2259.92
   360.1 2260.24   381.2 2260.58   401.6 2261.67   425.5 2261.87   432.2 2262.22
#Mann= 5, -1 ,  0
       0    0.05       0      40    0.08       0   190.8   0.045       0
  204.11    0.08       0  310.23    0.06       0
Bank Sta=190.8,204.11
XS Rating Curve= 0 ,0
Exp/Cntr(USF)=0,0
Exp/Cntr=0.3,0.1

Type RM Length L Ch R = 1 ,2034    ,197.4,198,196.1
XS GIS Cut Line= 4
 2392033.0591914714564.7202882222392110.57727858714560.308689765
2392145.20876457714467.0073260022391971.02719478714278.184409951
#Sta/Elev= 30
       0 2249.99     3.1 2250.06    59.2    2247   110.8 2243.89   131.1 2243.18
     145 2243.47   149.2 2242.38   152.72240.753   157.8 2239.76     162 2239.87
   164.72240.765   170.6 2243.82   174.7 2244.43   177.2 2243.98   179.7 2244.07
     196 2242.75   206.9 2242.34   225.9 2242.87   244.3 2244.36   272.2 2244.97
   293.9 2244.74   302.6 2245.71   314.4 2248.11   320.3 2248.91   348.4 2250.27
   359.2 2251.48   370.1 2252.24   375.6 2252.52   385.2 2252.16   434.1 2253.28
#Mann= 7, -1 ,  0
       0    0.08       0      50     0.1       0   152.7   0.045       0
   164.7     0.1       0  167.64    0.06       0  287.16     0.1       0
  427.16    0.05       0
#XS Ineff= 2 , 0
                          173.98         2246.73
Permanent Ineff=
       F       F
Bank Sta=152.7,164.7
XS Rating Curve= 0 ,0
Exp/Cntr(USF)=0,0
Exp/Cntr=0.3,0.1

Type RM Length L Ch R = 1 ,1836    ,222.7,231.6,239.4
XS GIS Cut Line= 4
 2392070.9002693714705.4406459292392251.93170968714645.848557211
2392268.05470415714581.352818457 2392182.6024666714404.804023395
#Sta/Elev= 30
       0 2245.76    22.4 2244.35    47.7 2243.29    68.7 2241.47    85.6 2241.12
   119.3 2239.67   136.1 2237.87   148.7 2235.87   152.9  2235.5   161.4 2235.29
     174 2235.45   191.3 2236.44   195.4 2235.84   200.92233.753   203.6 2233.01
  212.85 2233.75   224.3 2235.53   227.6  2235.7   232.5 2235.58   240.8 2234.51
     249 2234.64   253.1 2236.56   257.3 2237.27   261.7  2236.4   266.1 2236.13
   292.8 2237.33     355 2239.29   390.6 2239.55     435 2240.56   453.2 2241.35
#Mann= 5, -1 ,  0
       0    0.05       0      10     0.1       0   200.9   0.045       0
  212.85     0.1       0  377.07    0.05       0
#XS Ineff= 2 , 0
          190.24 2239.45
Permanent Ineff=
       F       F
Bank Sta=200.9,212.85
XS Rating Curve= 0 ,0
Exp/Cntr(USF)=0,0
Exp/Cntr=0.3,0.1

Type RM Length L Ch R = 1 ,1604    ,117,119,119.7
XS GIS Cut Line= 3
2392121.38462999714799.0067938592392396.00147894714779.435868879
2392390.79245891714518.175208669
#Sta/Elev= 30
       0 2242.64    15.6 2242.89    34.9 2241.66    42.9 2241.69    62.9 2240.52
      71 2240.51      75 2240.09      83  2238.4      99 2236.27   119.1 2232.96
   127.1 2232.04   147.2 2230.49   211.3 2229.34   235.4 2229.95   239.4 2229.55
   243.9 2228.64   258.32228.594   267.5 2227.54   271.5 2227.95     2732228.531
   275.3 2229.44   277.8 2229.61   308.7 2229.95   334.9 2228.36   349.6 2228.13
   393.6 2229.19   413.6 2229.18   441.1 2228.61   477.6 2228.76   536.6 2230.85
#Mann= 4, -1 ,  0
       0     0.1       0   258.3   0.045       0     273     0.1       0
  475.31    0.05       0
#XS Ineff= 2 , 0
           236.1 2231.45
Permanent Ineff=
       F       F
Bank Sta=258.3,273
XS Rating Curve= 0 ,0
Exp/Cntr(USF)=0,0
Exp/Cntr=0.3,0.1

Type RM Length L Ch R = 1 ,1485    ,428.5,421.4,411.9
XS GIS Cut Line= 3
2392168.75550263  714893.9637925  2392382.571796714895.163536029
2392658.08966992714711.306232073
#Sta/Elev= 30
       0 2240.13    15.4 2235.98    31.4  2232.3    35.4 2231.52    43.4 2230.73
    63.4  2229.5    83.4 2230.24   115.4 2230.08   143.4 2229.16   155.4 2229.68
   163.4 2231.18   169.2 2231.58   171.4 2231.51   175.4 2230.71   191.4 2226.57
   199.4 2226.49   201.3  2226.2   203.4 2225.87   207.4  2226.2   211.4 2227.08
   225.4 2226.26   249.4  2225.7   308.7 2225.22   379.2 2226.28   451.4 2228.72
   469.6 2228.83     484 2228.36   522.1 2228.29   530.8 2228.63   545.1 2230.19
#Mann= 5, -1 ,  0
       0     0.1       0   201.3   0.045       0   207.4     0.1       0
  323.82    0.05       0  443.82    0.06       0
Bank Sta=201.3,207.4
XS Rating Curve= 0 ,0
Exp/Cntr(USF)=0,0
Exp/Cntr=0.3,0.1

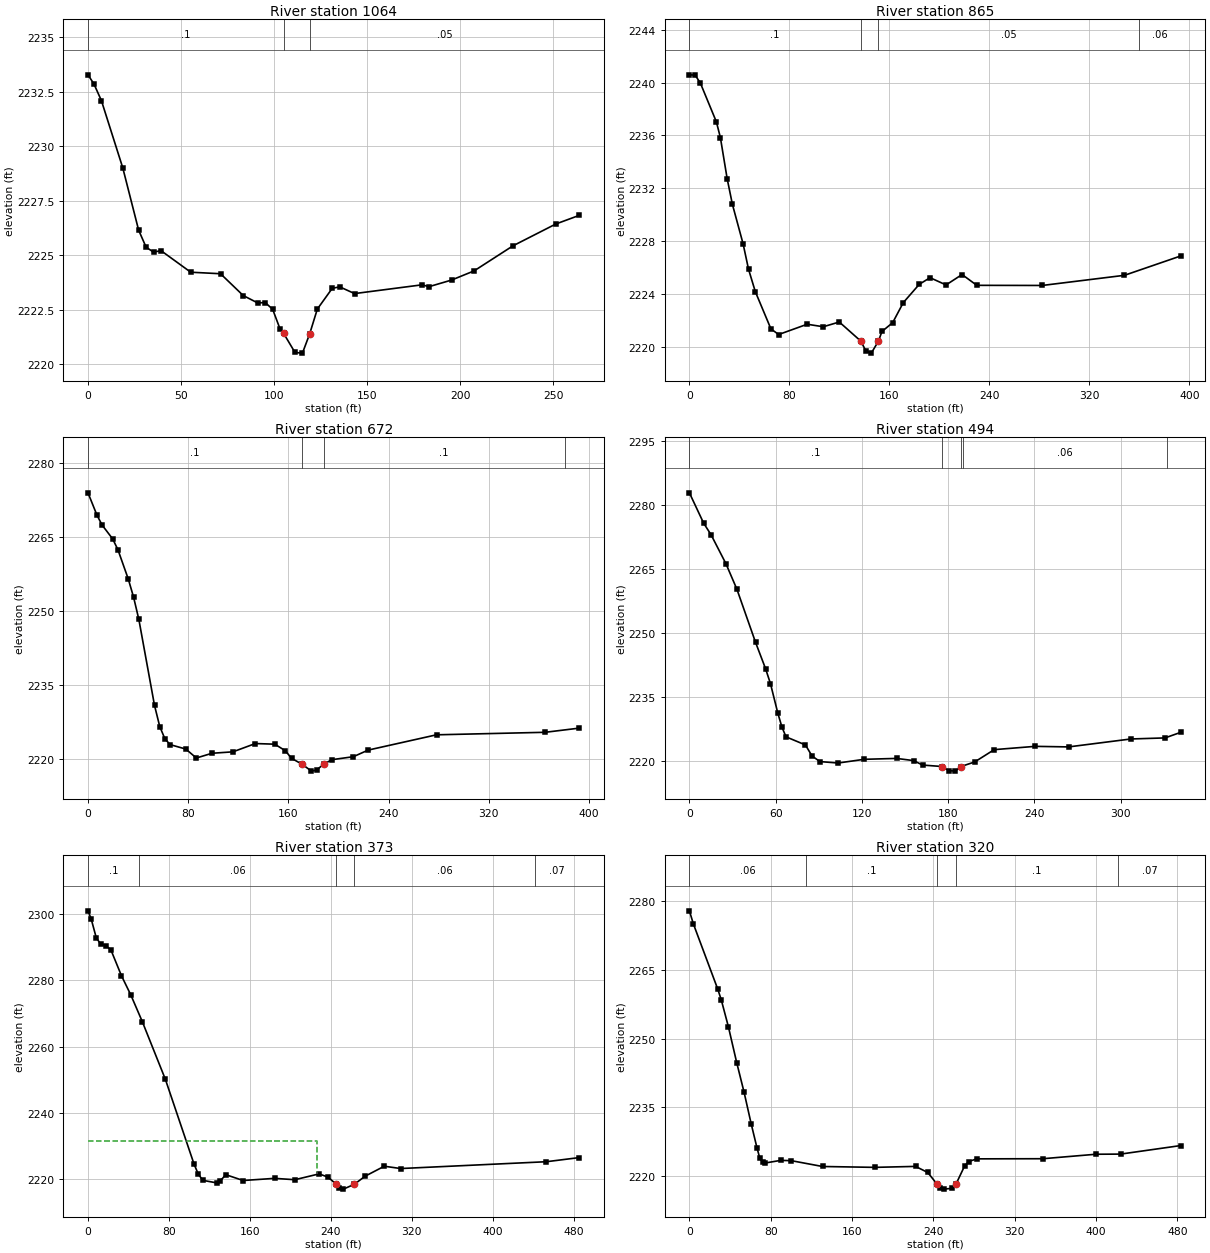
Type RM Length L Ch R = 1 ,1064    ,196.4,199.3,201.6
XS GIS Cut Line= 3
2392576.86549424 715272.374408322392575.43762245715139.049307854
2392569.51320425715008.537171711
#Sta/Elev= 30
       0 2233.27     3.2 2232.85     7.2 2232.09    18.7    2229    27.2 2226.15
    31.2 2225.37    35.2 2225.14    39.2 2225.21    55.2 2224.22    71.2 2224.15
    83.4 2223.15    91.2 2222.81    95.2 2222.83    99.2 2222.52   103.2 2221.61
  105.13 2221.41   111.2 2220.54   115.2 2220.51   119.12221.397   123.2 2222.53
   131.2 2223.48   135.2 2223.55   143.2 2223.24   179.3 2223.64   183.3 2223.56
   195.3 2223.86   207.4 2224.28   228.3 2225.43   251.3 2226.43     264 2226.83
#Mann= 3, -1 ,  0
       0     0.1       0  105.13   0.045       0   119.1    0.05       0
Bank Sta=105.13,119.1
XS Rating Curve= 0 ,0
Exp/Cntr(USF)=0,0
Exp/Cntr=0.3,0.1

Type RM Length L Ch R = 1 ,865     ,196.9,193,187.2
XS GIS Cut Line= 2
2392720.57616155715309.4426826792392858.36948708714941.263220832
#Sta/Elev= 30
       0  2240.6     4.6 2240.58     8.8 2239.97    21.6 2237.03    24.8 2235.84
    30.2 2232.73    34.4 2230.78      43 2227.77    47.3 2225.86    52.7 2224.17
    65.2 2221.34    71.4 2220.91    94.2 2221.69   107.1  2221.5   119.9 2221.86
  137.142220.409   141.2 2219.66   145.5  2219.5  151.222220.409     154 2221.14
   162.6 2221.81   171.1 2223.33   183.9 2224.72   192.5 2225.22   205.3 2224.67
   218.1 2225.46   229.9 2224.64   282.2 2224.63     348  2225.4   393.1 2226.87
#Mann= 4, -1 ,  0
       0     0.1       0  137.14   0.045       0  151.22    0.05       0
     360    0.06       0
Bank Sta=137.14,151.22
XS Rating Curve= 0 ,0
Exp/Cntr(USF)=0,0
Exp/Cntr=0.3,0.1

Type RM Length L Ch R = 1 ,672     ,179,177.7,175.2
XS GIS Cut Line= 3
 2393003.6444887715332.033891695 2392908.7857591715015.381291858
   2392916.60767714954.090760968
#Sta/Elev= 30
       0 2273.94     7.2 2269.39    11.3  2267.4    19.7  2264.6    23.9 2262.41
    32.2 2256.44    36.4 2252.79    40.6 2248.28    53.1 2230.86    57.3 2226.56
    61.4 2224.09    65.6 2222.91    78.1 2222.01    86.5  2220.2      99 2221.16
   115.7 2221.45   133.6 2223.13   149.1    2223   157.5 2221.68   162.5 2220.13
  170.82 2218.95   178.4 2217.54   182.5 2217.76   188.2 2218.96   194.7 2219.86
   211.8 2220.46   223.6  2221.8   278.2  2224.9     365 2225.41   392.3 2226.26
#Mann= 4, -1 ,  0
       0     0.1       0  170.82   0.045       0   188.2     0.1       0
  380.56    0.06       0
Bank Sta=170.82,188.2
XS Rating Curve= 0 ,0
Exp/Cntr(USF)=0,0
Exp/Cntr=0.3,0.1

Type RM Length L Ch R = 1 ,494     ,129.2,120.4,113.3
XS GIS Cut Line= 4
2393199.10826334715224.8383105962393154.50282991715170.197236407
2393088.34397853715045.2305171442392987.66097266714963.227009751
#Sta/Elev= 30
       0 2282.79     9.9 2275.68    15.1 2272.94    25.4 2266.18    33.1 2260.13
      46 2247.73      53 2241.52    56.4 2238.02    61.5 2231.11    64.4 2227.81
    67.2 2225.56    80.7 2223.66    85.3 2221.07    90.8 2219.76   103.4 2219.42
   121.5 2220.29   144.1  2220.5   155.9 2219.99   162.2 2218.94   175.8  2218.6
   180.3 2217.66   184.8 2217.52  188.85  2218.6   198.4 2219.67     212 2222.56
   240.5 2223.33   263.7  2223.2     307 2225.06   330.8 2225.31341.7871 2226.63
#Mann= 5, -1 ,  0
       0     0.1       0   175.8   0.045       0  188.85     0.1       0
  190.54    0.06       0  331.93    0.07       0
Bank Sta=175.8,188.85
XS Rating Curve= 0 ,0
Exp/Cntr(USF)=0,0
Exp/Cntr=0.3,0.1

Type RM Length L Ch R = 1 ,373     ,52.6,53.6,52.6
XS GIS Cut Line= 6
2393422.13628909715106.8007969482393356.17975028715026.021861888
2393328.32329215715010.6527815412393168.86908354715012.573916584
2393104.51105959715001.0471063242392988.12426345 714957.79344289
#Sta/Elev= 30
       0 2300.99     3.1  2298.6     8.2 2292.84    12.4 2291.04    17.6 2290.53
    22.7 2289.17    33.1  2281.4    42.3 2275.64    53.7 2267.56    76.5 2250.16
   104.9 2224.53   108.9 2221.67   113.4  2219.7   127.1 2218.93   130.9 2219.56
   136.2  2221.4   153.4 2219.64   184.4 2220.29   204.5 2219.88   228.5 2221.64
   237.3 2220.65  245.352218.528   248.5  2217.4   252.5 2217.04  263.43 2218.53
     274 2220.95   292.9 2223.95   309.1 2223.25   453.2 2225.31   485.8 2226.56
#Mann= 5, -1 ,  0
       0     0.1       0      50    0.06       0  245.35   0.045       0
  263.43    0.06       0  441.68    0.07       0
#XS Ineff= 2 , 0
          226.12 2231.66
Permanent Ineff=
       F       F
Bank Sta=245.35,263.43
XS Rating Curve= 0 ,0
Exp/Cntr(USF)=0,0
Exp/Cntr=0.3,0.1

Type RM Length L Ch R = 1 ,320     ,137.3,140.1,144.3
XS GIS Cut Line= 6
2393428.01412312715054.837830191 2393362.0575843714974.058895131
2393334.20112617714958.6898147832393213.16961844714966.374354957
2393110.38889361714949.0841395662392988.94829632714943.044830031
#Sta/Elev= 30
       0 2277.96     3.9 2275.11      28 2260.77    31.4 2258.45    38.3 2252.66
    46.5 2244.79    53.8 2238.27    60.8 2231.35    66.4 2226.19    69.3 2223.81
    72.1 2223.06    74.4 2222.81    89.9 2223.39   100.3 2223.32   130.9 2222.05
   182.3 2221.86   222.4 2222.07   234.4 2220.74   243.62218.179   246.4 2217.44
   250.4  2217.1   258.4 2217.28  262.142218.177   270.6 2222.14   274.6 2223.13
   282.7 2223.72   347.6 2223.75   399.9 2224.73     424 2224.76   483.3 2226.63
#Mann= 5, -1 ,  0
       0    0.06       0  114.29     0.1       0   243.6   0.045       0
  262.14     0.1       0  421.68    0.07       0
Bank Sta=243.6,262.14
XS Rating Curve= 0 ,0
Exp/Cntr(USF)=0,0
Exp/Cntr=0.3,0.1