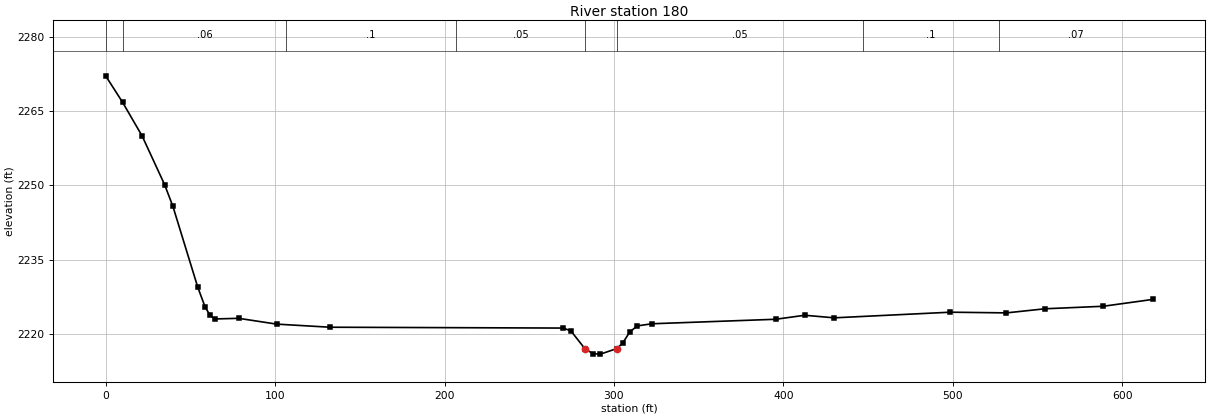
HEC-RAS study DRKFK_2T1.prj: DRKFK_2T1

--- DRKFK_2T1.g01 (geometry) --- (continued)

Type RM Length L Ch R = 1 ,180     ,,,
XS GIS Cut Line= 4
2393521.87746632 714981.440800732393483.02918284714927.212320157
2393253.06931814714827.9856951632392972.81313116714937.873388353
#Sta/Elev= 30
       0 2272.16      10  2266.8    21.5 2260.01    34.8 2250.15    39.7 2245.75
    54.4 2229.37    58.7 2225.41    61.6 2223.74    64.3 2222.99    78.5 2223.12
   100.9 2221.95   132.4 2221.32   270.2 2221.15   274.6 2220.57  282.842216.995
   287.6 2215.96     292 2215.88  301.642216.994   305.1 2218.08   309.4 2220.39
   313.8 2221.59   322.4 2222.02   395.5 2222.93   412.6 2223.74     430 2223.22
   498.6 2224.36   531.7 2224.22   554.4 2225.05   588.8 2225.56   618.2 2226.95
#Mann= 8, -1 ,  0
       0     0.1       0      10    0.06       0  106.71     0.1       0
  206.71    0.05       0  282.84   0.045       0  301.64    0.05       0
  447.16     0.1       0  527.16    0.07       0
Bank Sta=282.84,301.64
XS Rating Curve= 0 ,0
Exp/Cntr(USF)=0,0
Exp/Cntr=0.3,0.1
LCMann Table=0

Chan Stop Cuts=-1
Use User Specified Reach Order=0
Composite Channel Slope=5